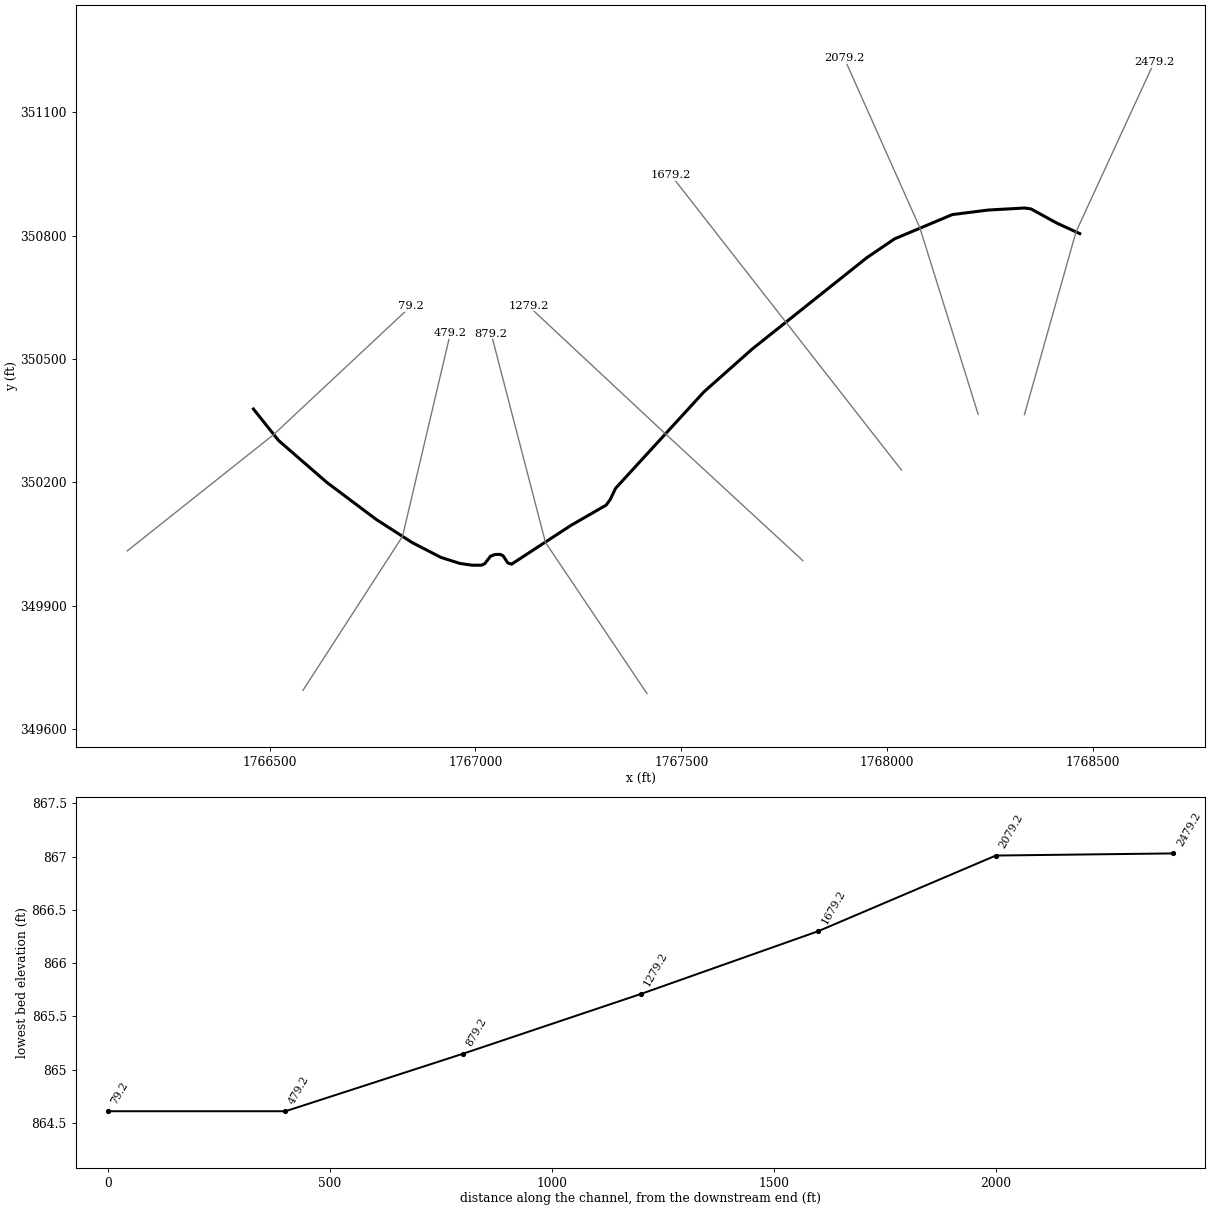
--- BthsRn2.prj (project) ---

Proj Title=BthsRn2
Current Plan=p01
Default Exp/Contr=0,0
English Units
Geom File=g01
Flow File=f01
Plan File=p01
BEGIN DESCRIPTION:
END DESCRIPTION:
DSS Export Rating Curves= 0
DSS Export Rating Curve Sorted= 0
DSS Export Volume Flow Curves= 0
DXF OffsetX= 0
DXF OffsetY= 0
DXF ScaleX= 0
DXF ScaleY= 0

--- BthsRn2.p01 (plan) ---

Plan Title=Floodplain
Program Version=4.00
Geom File=g01
Flow File=f01
K Sum by GR=0
Std Step Tol=0.01
Critical Tol=0.01
Num of Std Step Trials=20
Max Error Tol=0.3
Flow Tol Ratio=0.001
Split Flow NTrial=30
Split Flow Tol=0.02
Split Flow Ratio=0.02
Log Output Level=0
Friction Slope Method=1
Unsteady Friction Slope Method=2
Unsteady Bridges Friction Slope Method=1
Global Log Level=0
CheckData=False
Run HTab=0
Run UNet=0
Run PostProcess=0
UNET Theta=0
UNET Theta Warmup=0
UNET ZTol=0
UNET ZSATol=0
UNET MxIter=0
UNET MaxInSteps=0
UNET DtIC=0
UNET DtMin=0
UNET MaxCRTS=0
UNET WFStab=0
UNET SFStab=0
UNET WFX=0
UNET SFX=0
UNET DSS MLevel=0
UNET DZMax Abort=0
UNET Convert EG Bridges=0
UNET Use Existing IB Tables=0
UNET Froude Limit=0
UNET Froude Power=0
Write IC File=0
Echo Input=False
Echo Output=False
Write Detailed=0

--- BthsRn2.f01 (steady flow) ---

Flow Title=NFF Regression Equation
Program Version=4.00
Number of Profiles=1
Profile Names=P100yr
River Rch & RM=BthsRn2,Main      ,2479.2
6822.224
River Rch & RM=BthsRn2,Main      ,79.2
6836.073
River Rch & RM=BthsRn2,Main      ,79.2
6837.918
Boundary for River Rch & Prof#=BthsRn2,Main      ,1
Up Type=0
Dn Type=3
Dn Slope=0.006112

--- BthsRn2.g01 (geometry) ---

Geom Title=USGS 3m DEM
Program Version=4.00

River Reach=BthsRn2     ,Main
Reach XY= 30
     1768467.256      350805.339     1768411.069      350831.169
     1768349.050      350865.364     1768332.975      350867.628
     1768244.804      350862.646     1768157.815      350851.609
     1768017.672      350792.571     1767950.382      350746.819
     1767672.156      350524.682     1767555.035      350420.584
     1767340.270      350185.736     1767327.179      350158.484
     1767317.462      350144.823     1767231.538      350095.312
     1767087.796      350001.198     1767078.355      350004.326
     1767067.179      350021.634     1767060.011      350024.988
     1767047.512      350024.660     1767036.832      350020.776
     1767022.723      350002.508     1767014.693      349998.664
     1766991.216      349998.729     1766962.093      350002.990
     1766916.059      350017.705     1766845.821      350054.045
     1766759.031      350110.057     1766638.954      350200.283
     1766521.905      350302.149     1766460.994      350378.660

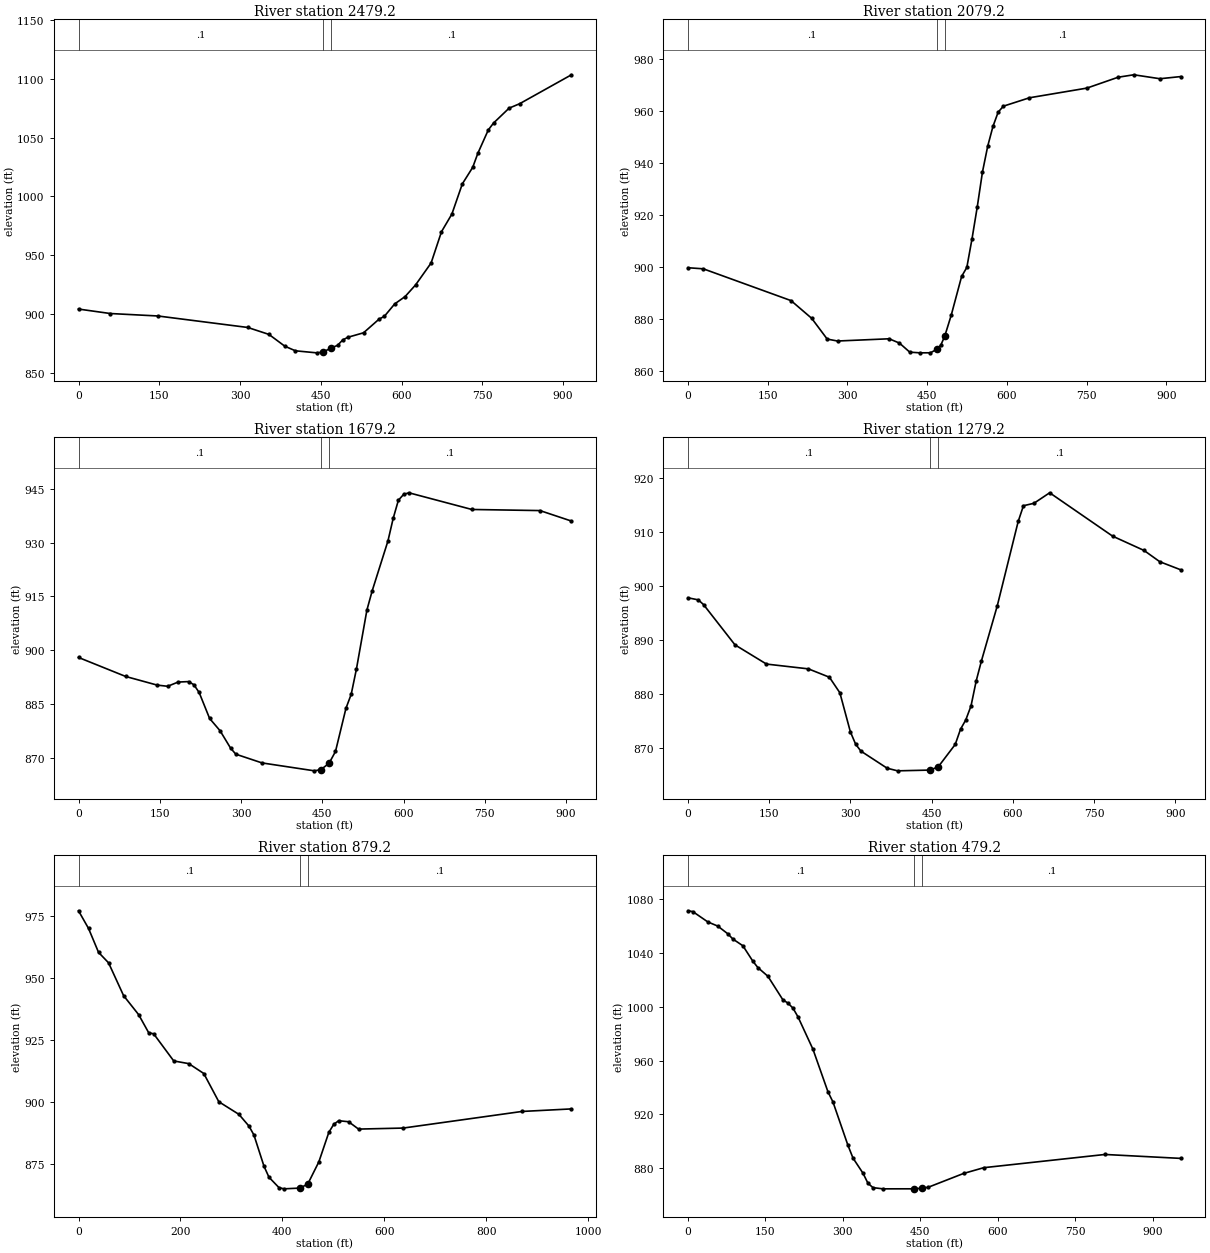
Type RM Length L Ch R = 1 ,2479.2,386.969,400,419.206
XS GIS Cut Line= 3
     1768332.956      350364.994     1768458.170      350809.516
     1768647.718      351221.830
#Sta/Elev= 30
       0  904.27    59.0  900.47   147.4  898.38   314.4  888.61   353.7  882.71
   383.2  872.67   402.9  868.76   442.2  867.03   454.3  867.76   469.3  871.12
   481.1  873.41   490.8  878.01   500.4  880.28   529.4  884.07   558.4  895.76
   568.0  898.04   587.3  908.64   606.6  914.89   626.0  924.76   654.9  943.44
   674.2  970.05   693.5  985.06   712.9 1010.73   732.2 1024.80   741.8 1036.81
   761.1 1056.58   770.8 1062.44   799.8 1075.15   819.1 1078.84   915.6 1103.52
#Mann= 3 , 0 , 0
       0     0.1       0   454.3   0.045       0   469.3     0.1       0
Bank Sta=   454.3,   469.3
Exp/Cntr=0.3,0.1

Type RM Length L Ch R = 1 ,2079.2,391.878,400,405.493
XS GIS Cut Line= 3
     1768220.600      350365.770     1768078.947      350819.838
     1767895.446      351232.208
#Sta/Elev= 30
       0  899.77    29.1  899.35   194.1  887.11   233.0  880.29   262.1  872.31
   281.5  871.56   378.6  872.42   398.0  870.76   417.4  867.27   436.8  867.01
   456.2  867.03   468.1  868.34   475.7  869.96   483.1  873.39   495.3  881.46
   514.9  896.42   524.7  899.88   534.5  910.96   544.3  923.17   554.1  936.62
   564.0  946.58   573.8  954.13   583.6  959.64   593.4  961.94   642.5  965.18
   750.4  968.90   809.3  973.09   838.7  974.03   887.8  972.51   927.0  973.34
#Mann= 3 , 0 , 0
       0     0.1       0   468.1   0.045       0   483.1     0.1       0
Bank Sta=   468.1,   483.1
Exp/Cntr=0.3,0.1

Type RM Length L Ch R = 1 ,1679.2,396.347,400,403.523
XS GIS Cut Line= 3
     1768034.344      350230.127     1767754.554      350588.934
     1767474.764      350947.741
#Sta/Elev= 30
       0  897.96    87.1  892.65   145.2  890.24   164.6  889.91   183.9  891.09
   203.3  891.22   213.0  890.34   222.7  888.18   242.0  880.93   261.4  877.48
   280.7  872.65   290.4  870.95   338.8  868.51   435.6  866.30   447.5  866.66
   462.5  868.40   474.4  871.71   493.7  883.75   503.4  887.68   513.1  894.76
   532.4  911.20   542.1  916.54   571.2  930.47   580.9  936.79   590.5  941.86
   600.2  943.49   609.9  943.94   726.1  939.28   851.9  938.97   910.0  936.04
#Mann= 3 , 0 , 0
       0     0.1       0   447.5   0.045       0   462.5     0.1       0
Bank Sta=   447.5,   462.5
Exp/Cntr=0.3,0.1

Type RM Length L Ch R = 1 ,1279.2,405.325,400,386.931
XS GIS Cut Line= 3
     1767794.870      350009.765     1767460.794      350318.660
     1767128.499      350629.487
#Sta/Elev= 30
       0  897.79    19.4  897.40    29.0  896.53    87.1  889.06   145.2  885.50
   222.7  884.61   261.4  883.06   280.7  880.18   300.1  872.94   309.8  870.65
   319.5  869.37   367.9  866.20   387.2  865.71   447.5  865.85   462.5  866.48
   493.7  870.61   503.4  873.42   513.1  875.14   522.8  877.74   532.4  882.39
   542.1  886.11   571.2  896.27   609.9  911.94   619.6  914.85   638.9  915.30
   668.0  917.25   784.2  909.21   842.2  906.56   871.3  904.47   910.0  902.97
#Mann= 3 , 0 , 0
       0     0.1       0   447.5   0.045       0   462.5     0.1       0
Bank Sta=   447.5,   462.5
Exp/Cntr=0.3,0.1

Type RM Length L Ch R = 1 ,879.2,426.076,400,384.44
XS GIS Cut Line= 3
     1767416.542      349686.378     1767170.023      350054.069
     1767038.174      350562.030
#Sta/Elev= 30
       0  977.16    19.7  970.04    39.3  960.42    59.0  956.19    88.5  942.97
   118.0  935.33   137.7  928.05   147.6  927.58   186.9  916.67   216.4  915.59
   245.9  911.61   275.4  900.23   314.8  895.16   334.5  890.44   344.3  886.84
   364.0  874.29   373.8  869.83   393.5  865.63   403.3  865.15   435.2  865.46
   450.2  867.17   471.8  876.06   491.3  887.90   501.0  891.16   510.7  892.59
   530.1  892.18   549.6  889.22   637.1  889.63   870.3  896.32   967.5  897.35
#Mann= 3 , 0 , 0
       0     0.1       0   435.2   0.045       0   450.2     0.1       0
Bank Sta=   435.2,   450.2
Exp/Cntr=0.3,0.1

Type RM Length L Ch R = 1 ,479.2,407.332,400,386.475
XS GIS Cut Line= 3
     1766581.342      349694.419     1766822.956      350068.802
     1766939.305      350563.700
#Sta/Elev= 30
       0 1071.55     9.7 1070.94    38.7 1063.26    58.1 1060.13    77.5 1054.39
    87.2 1050.52   106.6 1045.51   125.9 1034.02   135.6 1029.28   155.0 1022.82
   184.0 1005.28   193.7 1002.87   203.4  999.15   213.1  992.71   242.2  968.49
   271.2  936.87   280.9  929.28   310.0  896.90   319.7  887.50   339.0  876.26
   348.7  868.73   358.4  865.50   377.8  864.61   438.1  864.63   453.1  865.08
   465.1  865.76   533.6  876.05   572.7  880.35   807.3  890.19   954.0  887.27
#Mann= 3 , 0 , 0
       0     0.1       0   438.1   0.045       0   453.1     0.1       0
Bank Sta=   438.1,   453.1
Exp/Cntr=0.3,0.1

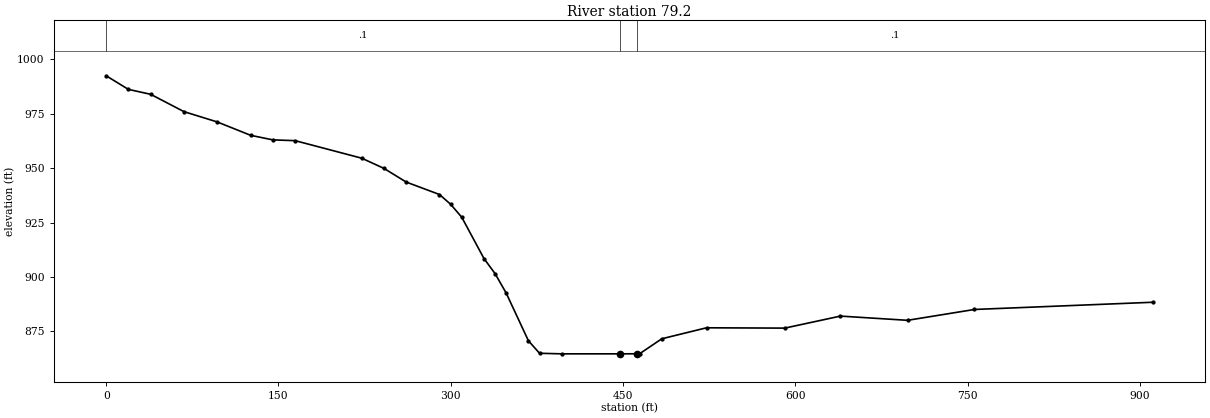
Type RM Length L Ch R = 1 ,79.2,79.243,79.243,77.421
XS GIS Cut Line= 3
     1766154.630      350033.472     1766510.350      350316.664
     1766843.600      350629.106
#Sta/Elev= 30
       0  992.50    19.3  986.25    38.7  983.98    67.7  976.01    96.7  971.26
   125.8  965.11   145.1  963.02   164.5  962.66   222.5  954.59   241.9  949.89
   261.2  943.62   290.2  937.89   299.9  933.39   309.6  927.42   328.9  908.46
   338.6  901.50   348.3  892.52   367.6  870.64   377.3  864.87   396.6  864.61
   447.2  864.61   462.2  864.64   464.4  864.65   483.8  871.55   522.7  876.59
   590.8  876.44   639.3  881.97   697.7  880.03   756.0  885.02   911.5  888.34
#Mann= 3 , 0 , 0
       0     0.1       0   447.2   0.045       0   462.2     0.1       0
Bank Sta=   447.2,   462.2
Exp/Cntr=0.3,0.1